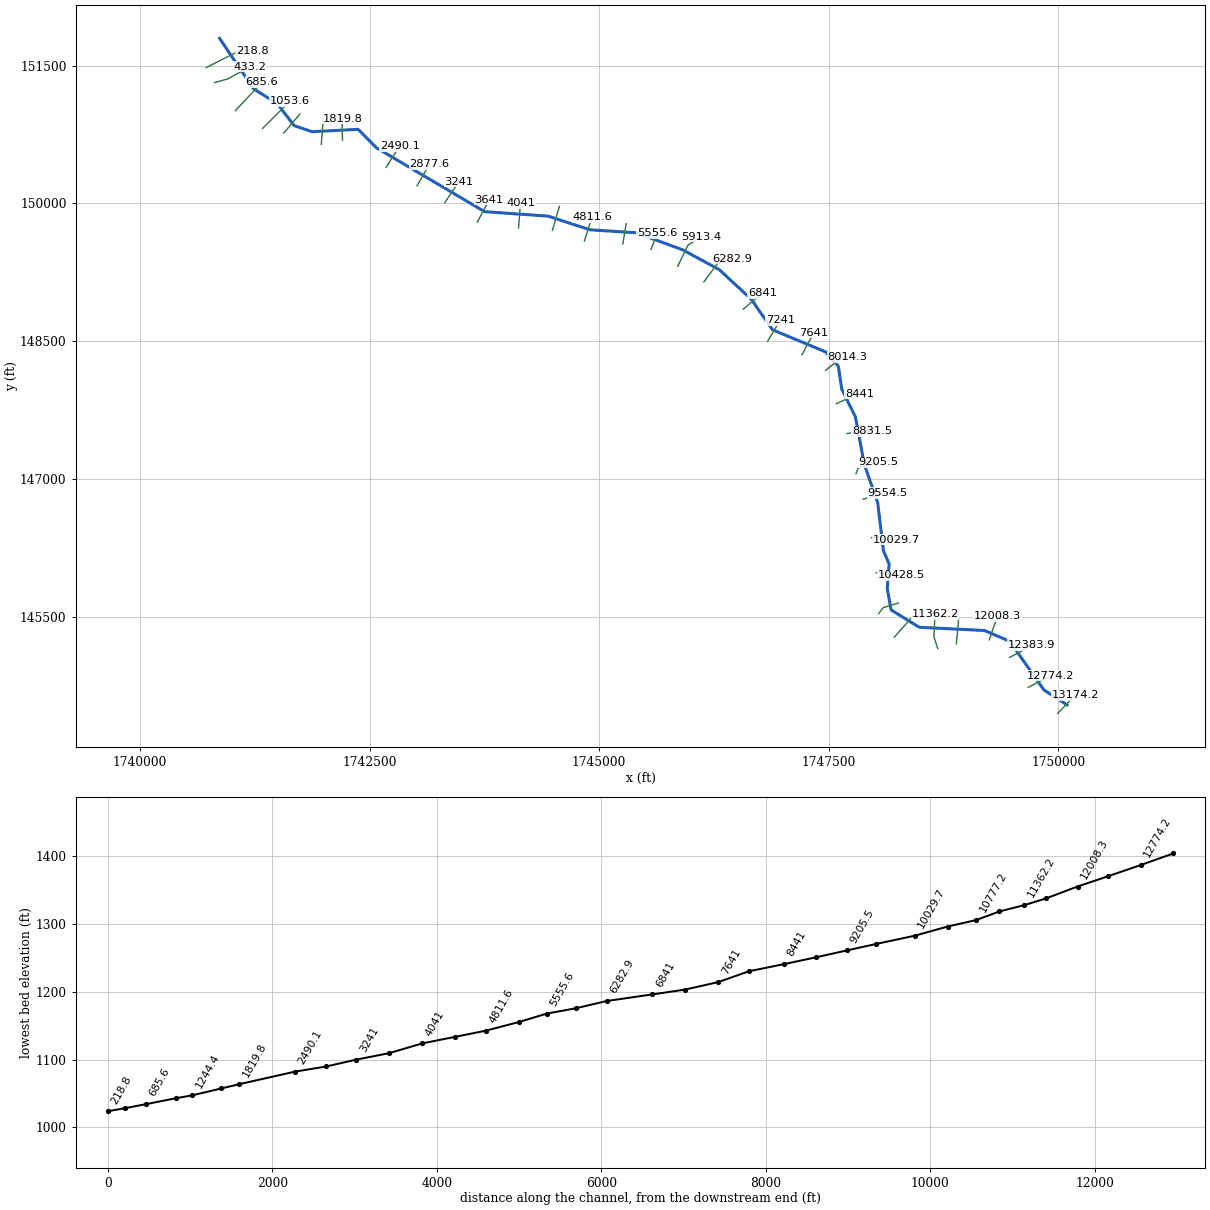
--- Crane Creek.prj (project) ---

Proj Title=Crane Creek
Current Plan=p01
Default Exp/Contr=0,0
English Units
Geom File=g01
Flow File=f01
Plan File=p01
BEGIN DESCRIPTION:
END DESCRIPTION:
DSS Export Rating Curves= 0
DSS Export Rating Curve Sorted= 0
DSS Export Volume Flow Curves= 0
DXF OffsetX= 0
DXF OffsetY= 0
DXF ScaleX= 0
DXF ScaleY= 0

--- Crane Creek.p01 (plan) ---

Plan Title=Floodplain
Program Version=4.00
Geom File=g01
Flow File=f01
K Sum by GR=0
Std Step Tol=0.01
Critical Tol=0.01
Num of Std Step Trials=20
Max Error Tol=0.3
Flow Tol Ratio=0.001
Split Flow NTrial=30
Split Flow Tol=0.02
Split Flow Ratio=0.02
Log Output Level=0
Friction Slope Method=1
Unsteady Friction Slope Method=2
Unsteady Bridges Friction Slope Method=1
Global Log Level=0
CheckData=False
Run HTab=0
Run UNet=0
Run PostProcess=0
UNET Theta=0
UNET Theta Warmup=0
UNET ZTol=0
UNET ZSATol=0
UNET MxIter=0
UNET MaxInSteps=0
UNET DtIC=0
UNET DtMin=0
UNET MaxCRTS=0
UNET WFStab=0
UNET SFStab=0
UNET WFX=0
UNET SFX=0
UNET DSS MLevel=0
UNET DZMax Abort=0
UNET Convert EG Bridges=0
UNET Use Existing IB Tables=0
UNET Froude Limit=0
UNET Froude Power=0
Write IC File=0
Echo Input=False
Echo Output=False
Write Detailed=0

--- Crane Creek.f01 (steady flow) ---

Flow Title=NFF Regression Equation
Program Version=4.00
Number of Profiles=1
Profile Names=P100yr
River Rch & RM=Crane Creek,Main      ,13174.2
848.9319
River Rch & RM=Crane Creek,Main      ,11362.2
941.7477
River Rch & RM=Crane Creek,Main      ,11059.1
1216.049
River Rch & RM=Crane Creek,Main      ,10029.7
1322.378
River Rch & RM=Crane Creek,Main      ,6282.9
1468.515
River Rch & RM=Crane Creek,Main      ,5913.4
1912.983
River Rch & RM=Crane Creek,Main      ,218.8
2075.066
Boundary for River Rch & Prof#=Crane Creek,Main      ,1
Up Type=0
Dn Type=3
Dn Slope=0.023463

--- Crane Creek.g01 (geometry) ---

Geom Title=Geometry
Program Version=4.00

River Reach=Crane Creek     ,Main
Reach XY= 30
     1750096.131      144537.136     1749843.474      144701.382
     1749472.288      145229.902     1749196.211      145348.221
     1748486.569      145383.255      1748179.84      145571.968
     1748137.615      145804.466     1748158.395       146072.45
     1748096.601      146216.782     1748033.234      146743.047
      1747888.75      147152.724     1747790.725      147674.263
      1747642.21      147977.908     1747604.581      148227.054
      1747466.61      148382.699     1746887.571      148623.456
     1746657.029      148955.107      1746308.11       149278.37
     1745911.301      149493.878     1745401.607       149680.31
     1744899.564        149712.8     1744446.072       149861.04
     1743752.227      149910.071     1742576.623      150603.917
     1742374.499      150806.842     1741874.225      150780.657
     1741678.671      150847.362     1741492.239      151086.815
     1741233.971      151249.872     1740866.025      151797.707

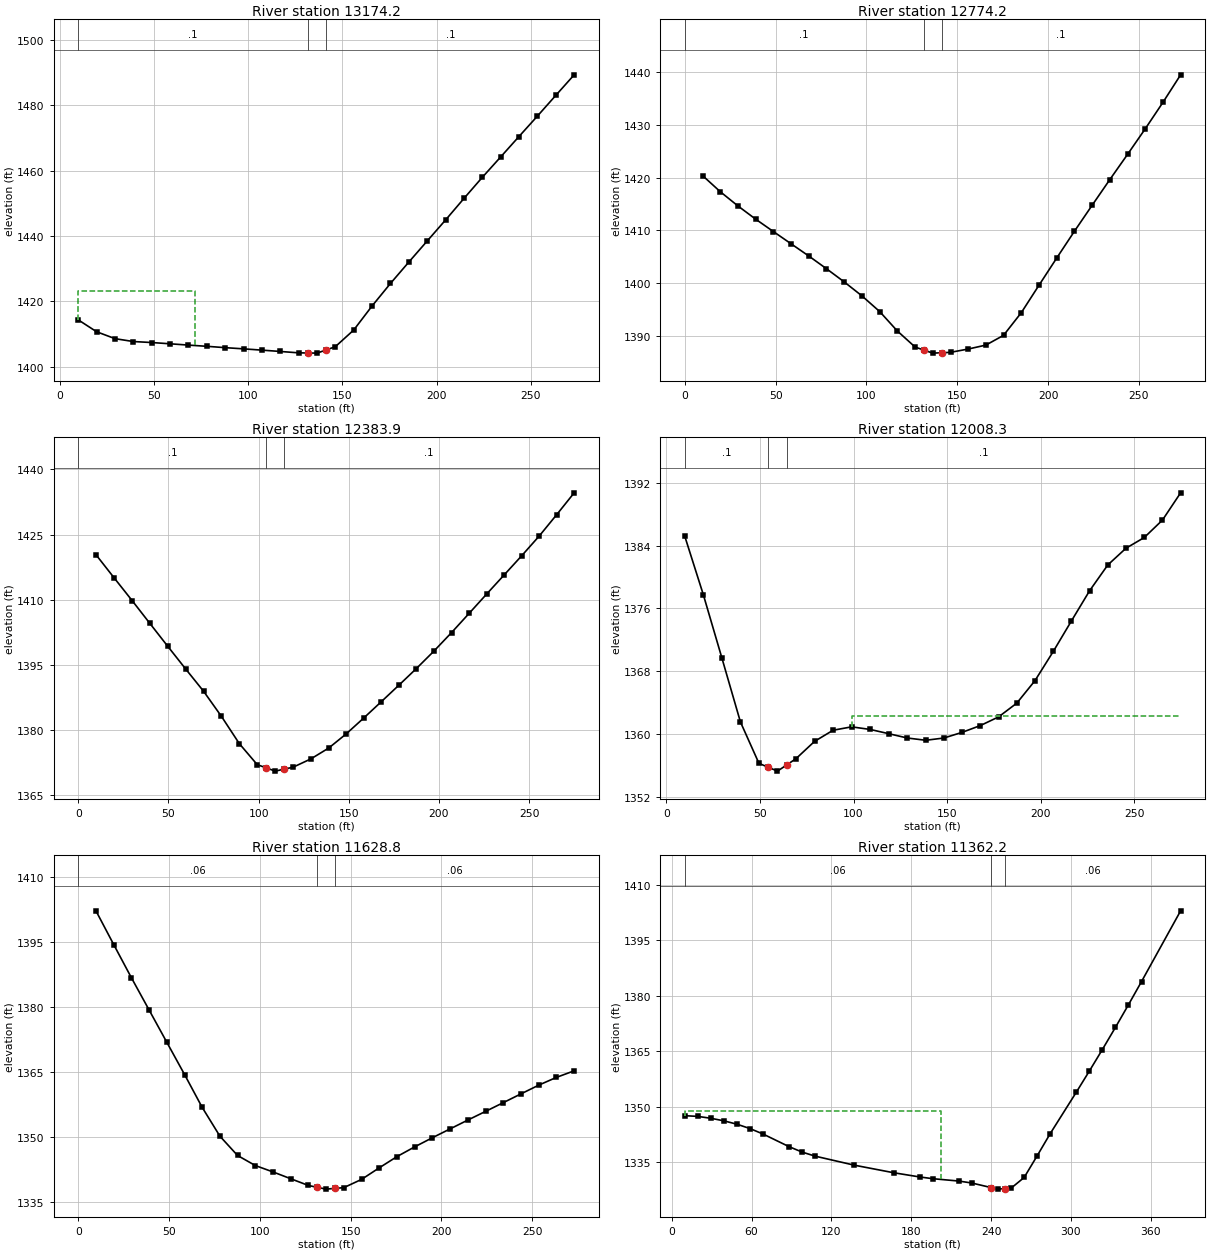
Type RM Length L Ch R = 1 ,13174.2 ,406.7,400,393.2
XS GIS Cut Line= 3
     1749994.361       144445.62     1750088.919      144544.064
     1750183.476      144642.508
#Sta/Elev= 30
     9.8 1414.28    19.5 1410.65    29.3 1408.53      39 1407.65    48.7 1407.35
    58.5 1406.96    68.2 1406.56      78 1406.19    87.7 1405.78    97.5 1405.41
   107.2 1405.02     117 1404.61   126.7 1404.19   131.5 1404.15   136.5  1404.1
   141.5 1405.11   146.2 1406.06     156 1411.19   165.7 1418.53   175.5 1425.46
   185.2 1431.98     195 1438.47   204.8 1444.94   214.5  1451.5   224.2 1457.94
     234 1464.22   243.7 1470.47   253.5 1476.74   263.2 1483.05     273 1489.38
#Mann= 3 , 0 , 0
     9.8      .1       0   131.5    .045       0   141.5      .1       0
#XS Ineff= 2 , 0
           71.98 1423.25
Permanent Ineff=
       F       F
Bank Sta=131.5,141.5
XS Rating Curve= 0 ,0
Exp/Cntr=0.3,0.1

Type RM Length L Ch R = 1 ,12774.2 ,390.7,390.3,390
XS GIS Cut Line= 3
     1749672.827      144728.974     1749793.976      144791.865
     1749915.306      144854.406
#Sta/Elev= 30
     9.8 1420.36    19.5 1417.33    29.3 1414.62      39 1412.14    48.8 1409.79
    58.5 1407.49    68.3 1405.17      78 1402.78    87.8 1400.28    97.5 1397.66
   107.3 1394.69     117 1391.03   126.8 1387.99   131.5 1387.43   136.5 1386.84
   141.5 1386.91   146.3 1386.99     156 1387.61   165.8 1388.36   175.5  1390.2
   185.3 1394.49     195 1399.65   204.8 1404.81   214.5 1409.84   224.3 1414.77
     234  1419.6   243.8 1424.38   253.5 1429.19   263.3 1434.21     273 1439.39
#Mann= 3 , 0 , 0
       0      .1       0   131.5    .045       0   141.5      .1       0
Bank Sta=131.5,141.5
XS Rating Curve= 0 ,0
Exp/Cntr=0.3,0.1

Type RM Length L Ch R = 1 ,12383.9 ,359.9,375.6,391.3
XS GIS Cut Line= 3
     1749469.428      145054.893     1749592.807      145118.754
     1749708.196      145190.872
#Sta/Elev= 30
     9.9 1420.33    19.8 1415.09    29.8 1409.85    39.7 1404.57    49.6 1399.31
    59.5 1394.11    69.5 1388.95    79.4 1383.17    89.3 1376.91    99.2 1372.09
   104.2 1371.34   109.2 1370.59   114.2 1371.05   119.1 1371.49     129 1373.41
   138.9 1375.91   148.6 1379.17   158.4 1382.85   168.1 1386.59   177.8 1390.37
   187.5  1394.2   197.2  1398.2     207 1402.47   216.7 1406.87   226.4 1411.31
   236.1  1415.7   245.8  1420.1   255.6 1424.68   265.3  1429.6     275 1434.63
#Mann= 3 , 0 , 0
       0      .1       0   104.2    .045       0   114.2      .1       0
Bank Sta=104.2,114.2
XS Rating Curve= 0 ,0
Exp/Cntr=0.3,0.1

Type RM Length L Ch R = 1 ,12008.3 ,375.5,379.5,384.1
XS GIS Cut Line= 3
     1749249.835      145246.639     1749293.758      145378.084
     1749339.923      145506.147
#Sta/Elev= 30
     9.9 1385.18    19.8 1377.74    29.7 1369.69    39.6 1361.54    49.5 1356.26
    54.4 1355.77    59.4 1355.27    64.4 1356.07    69.3 1356.86    79.2 1359.06
    89.1 1360.48      99 1360.91   108.9 1360.58   118.8 1360.04   128.7 1359.49
   138.6  1359.2   148.3 1359.49     158 1360.21   167.8 1361.08   177.5 1362.18
   187.2 1363.93   196.9 1366.79   206.7 1370.52   216.4 1374.41   226.1 1378.25
   235.8 1381.53   245.5 1383.66   255.3 1385.03     265 1387.25   274.7 1390.72
#Mann= 3 , 0 , 0
     9.9      .1       0    54.4    .045       0    64.4      .1       0
#XS Ineff= 2 , 0
                           99.16         1362.23
Permanent Ineff=
       F       F
Bank Sta=54.4,64.4
XS Rating Curve= 0 ,0
Exp/Cntr=0.3,0.1

Type RM Length L Ch R = 1 ,11628.8 ,265.3,266.6,267.3
XS GIS Cut Line= 3
     1748889.452      145203.557     1748904.043      145339.261
     1748914.456      145475.442
#Sta/Elev= 30
     9.7 1402.22    19.5 1394.41    29.2 1386.77      39 1379.28    48.7 1371.86
    58.5 1364.38    68.2 1356.79      78 1350.11    87.7 1345.66    97.5 1343.33
   107.2 1341.86     117 1340.28   126.7 1338.73   131.5 1338.31   136.5 1337.88
   141.5 1338.06   146.2 1338.22     156 1340.13   165.8 1342.82   175.5  1345.4
   185.3 1347.66     195 1349.76   204.8 1351.81   214.5 1353.84   224.3 1355.85
     234 1357.86   243.8  1359.9   253.6 1361.92   263.3 1363.71   273.1 1365.23
#Mann= 3 , 0 , 0
       0     .06       0   131.5    .045       0   141.5     .06       0
Bank Sta=131.5,141.5
XS Rating Curve= 0 ,0
Exp/Cntr=0.3,0.1

Type RM Length L Ch R = 1 ,11362.2 ,316.8,303.1,289.3
XS GIS Cut Line= 3
     1748686.973      145152.491     1748645.464      145283.327
     1748658.187      145528.181
#Sta/Elev= 30
     9.8 1347.62    19.6 1347.43    29.4 1346.92    39.2 1346.23      49 1345.32
    58.8 1344.14    68.6 1342.67    88.2 1339.25      98 1337.79   107.8 1336.69
   137.3 1334.25   166.7 1332.22   186.3 1331.08   196.1 1330.61   215.7 1329.97
   225.5 1329.44   240.1  1328.2   245.1 1327.79   250.1 1327.92     255 1328.05
   264.8 1330.93   274.6 1336.79   284.4 1342.78     304 1353.96   313.8 1359.67
   323.6 1365.49   333.4 1371.46   343.2 1377.58     353 1383.83   382.4 1402.94
#Mann= 3 , 0 , 0
     9.8     .06       0   240.1    .045       0   250.1     .06       0
#XS Ineff= 2 , 0
          202.68 1348.78
Permanent Ineff=
       F       F
Bank Sta=240.1,250.1
XS Rating Curve= 0 ,0
Exp/Cntr=0.3,0.1

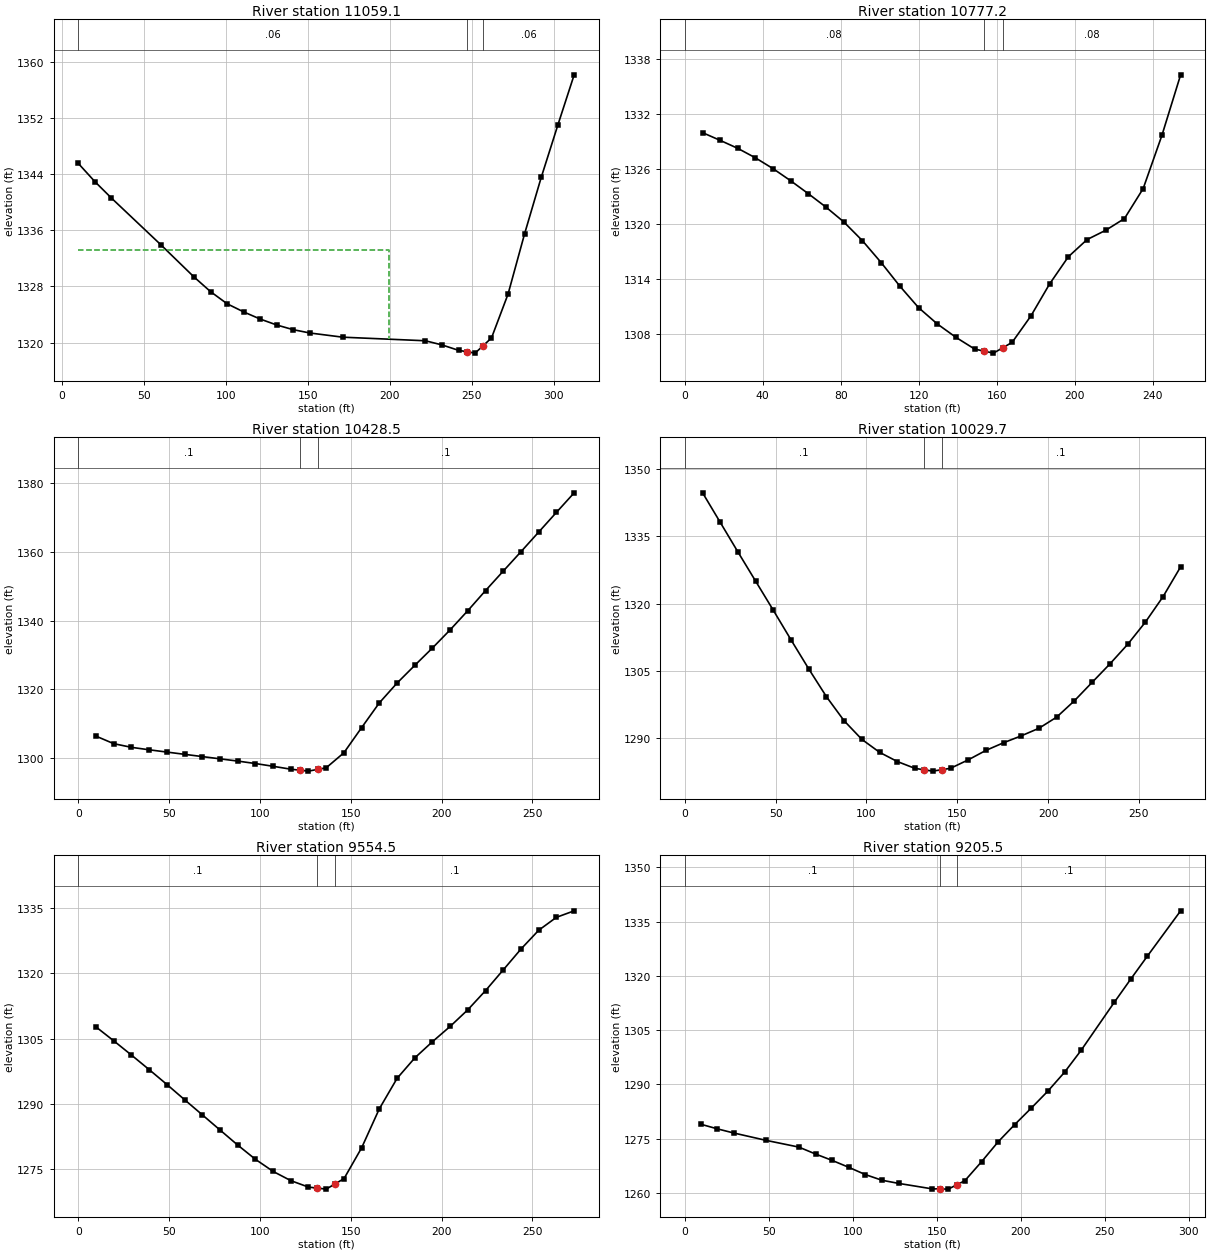
Type RM Length L Ch R = 1 ,11059.1 ,294.3,282,269.6
XS GIS Cut Line= 2
     1748214.094      145275.851     1748421.584      145509.446
#Sta/Elev= 25
    10.1 1345.51    20.2 1342.92    30.2  1340.6    60.5 1333.91    80.6 1329.35
    90.7 1327.26   100.8 1325.53   110.9 1324.37   120.9 1323.36     131 1322.51
   141.1 1321.84   151.2 1321.37   171.3 1320.77   221.7 1320.26   231.8 1319.67
   241.9  1318.9     247  1318.7     252  1318.5     257 1319.58     262 1320.66
   272.1 1326.91   282.2 1335.51   292.3 1343.51   302.4 1350.94   312.4 1358.13
#Mann= 3 , 0 , 0
    10.1     .06       0     247    .045       0     257     .06       0
#XS Ineff= 2 , 0
          199.66 1333.25
Permanent Ineff=
       F       F
Bank Sta=247,257
XS Rating Curve= 0 ,0
Exp/Cntr=0.3,0.1

Type RM Length L Ch R = 1 ,10777.2 ,356.6,348.7,340.9
XS GIS Cut Line= 3
     1748044.026       145532.39      1748093.28      145597.315
     1748258.951      145646.569
#Sta/Elev= 29
     9.1 1329.96    18.1 1329.12    27.2 1328.24    36.2 1327.21    45.3 1326.02
    54.3  1324.7    63.4 1323.28    72.4 1321.82    81.5 1320.21    91.1 1318.15
   100.7 1315.76   110.3 1313.18   119.9 1310.83   129.5 1309.05   139.1 1307.58
   148.7  1306.3   153.3 1306.09   158.3 1305.86   163.3 1306.47   167.9 1307.04
   177.5 1309.92   187.1 1313.42   196.7 1316.39   206.3 1318.27   215.9 1319.29
   225.5 1320.57   235.1 1323.85   244.7 1329.66   254.3 1336.28
#Mann= 3 , 0 , 0
       0     .08       0   153.3    .045       0   163.3     .08       0
Bank Sta=153.3,163.3
XS Rating Curve= 0 ,0
Exp/Cntr=0.3,0.1

Type RM Length L Ch R = 1 ,10428.5 ,398.4,398.7,399.1
XS GIS Cut Line= 3
     1748017.514      145977.398     1748153.389      145964.348
     1748289.263      145951.298
#Sta/Elev= 30
     9.8 1306.37    19.5 1304.19    29.2 1303.13      39 1302.41    48.7 1301.75
    58.5 1301.09    68.3 1300.43      78 1299.78    87.7 1299.13    97.5 1298.41
   107.2 1297.61     117 1296.76   121.8 1296.48   126.7  1296.2   131.8 1296.71
   136.5 1297.18   146.2 1301.53     156 1308.88   165.7 1316.05   175.5 1321.84
   185.3 1327.02     195 1332.06   204.7 1337.31   214.5 1342.94   224.2 1348.75
     234 1354.45   243.8 1360.12   253.5  1365.8   263.2  1371.5     273 1377.21
#Mann= 3 , 0 , 0
       0      .1       0   121.8    .045       0   131.8      .1       0
Bank Sta=121.8,131.8
XS Rating Curve= 0 ,0
Exp/Cntr=0.3,0.1

Type RM Length L Ch R = 1 ,10029.7 ,468.7,475.2,481.7
XS GIS Cut Line= 3
     1747964.538      146360.695     1748100.609      146349.882
      1748236.68      146339.068
#Sta/Elev= 30
     9.8  1344.7    19.5 1338.13    29.2 1331.56      39 1325.02    48.8 1318.49
    58.5 1311.93    68.3 1305.43      78 1299.27    87.7 1293.92    97.5 1289.76
   107.3 1286.87     117 1284.83   126.7 1283.31   131.5    1283   136.5 1282.69
   141.5 1283.01   146.3 1283.32     156 1285.19   165.8 1287.31   175.5 1289.01
   185.3 1290.56     195 1292.24   204.8 1294.74   214.5 1298.36   224.2 1302.44
     234 1306.55   243.8 1310.92   253.5 1315.84   263.3 1321.55     273 1328.21
#Mann= 3 , 0 , 0
       0      .1       0   131.5    .045       0   141.5      .1       0
Bank Sta=131.5,141.5
XS Rating Curve= 0 ,0
Exp/Cntr=0.3,0.1

Type RM Length L Ch R = 1 ,9554.5  ,348.5,349,349.5
XS GIS Cut Line= 3
     1747875.784      146779.632     1748008.131      146813.046
     1748140.478      146846.461
#Sta/Elev= 30
     9.8 1307.64    19.5 1304.47    29.2 1301.21      39 1297.85    48.8 1294.42
    58.5 1290.93    68.3 1287.44      78 1283.97    87.7 1280.52    97.5 1277.23
   107.3 1274.43     117 1272.32   126.7 1270.84   131.5 1270.61   136.5 1270.37
   141.5 1271.61   146.3 1272.79     156 1279.88   165.7 1288.82   175.5 1295.84
   185.3 1300.56     195 1304.28   204.8 1307.81   214.5 1311.63   224.2 1316.01
     234  1320.8   243.8 1325.61   253.5  1329.9   263.2 1332.86     273 1334.36
#Mann= 3 , 0 , 0
       0      .1       0   131.5    .045       0   141.5      .1       0
Bank Sta=131.5,141.5
XS Rating Curve= 0 ,0
Exp/Cntr=0.3,0.1

Type RM Length L Ch R = 1 ,9205.5  ,377.5,374,370.5
XS GIS Cut Line= 3
     1747797.366      147055.662     1747821.586      147119.142
     1748040.455      147179.906
#Sta/Elev= 27
     9.7 1278.94    19.4 1277.68    29.1 1276.54    48.5 1274.49    67.9 1272.64
    77.8 1270.73    87.7 1268.96    97.6 1267.05   107.4 1265.05   117.3 1263.48
   127.2 1262.61     147 1261.11   151.8 1261.07   156.8 1261.02   161.8  1262.2
   166.7 1263.36   176.6 1268.58   186.5  1274.1   196.3 1278.84   206.2 1283.42
   216.1 1288.12     226 1293.33   235.8 1299.35   255.6 1312.66   265.5 1319.14
   275.3 1325.43   295.1 1337.96
#Mann= 3 , 0 , 0
       0      .1       0   151.8    .045       0   161.8      .1       0
Bank Sta=151.8,161.8
XS Rating Curve= 0 ,0
Exp/Cntr=0.3,0.1

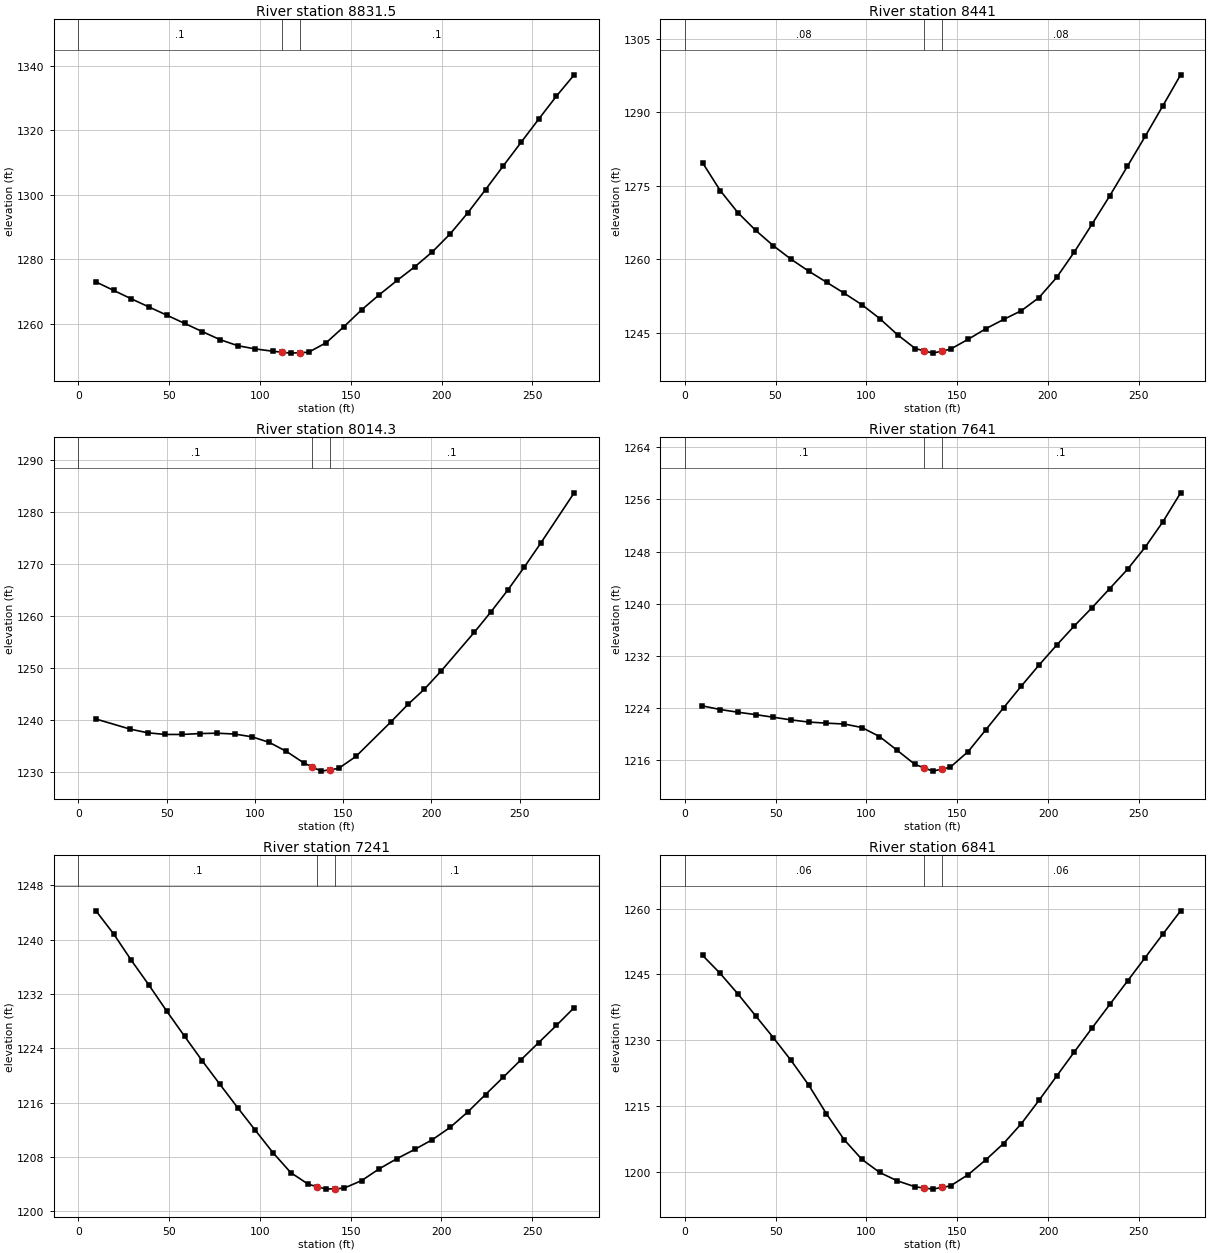
Type RM Length L Ch R = 1 ,8831.5  ,383.8,390.5,396.3
XS GIS Cut Line= 3
     1747698.083       147493.98     1747833.968      147506.922
     1747969.853      147519.863
#Sta/Elev= 30
     9.8 1272.92    19.5 1270.31    29.2 1267.71      39 1265.16    48.8 1262.63
    58.5  1260.1    68.3 1257.55      78 1255.07    87.8 1253.19    97.5 1252.18
   107.3 1251.46     112 1251.18     117 1250.89     122 1251.03   126.8 1251.17
   136.5 1254.13   146.3 1259.12     156 1264.32   165.8 1269.03   175.5 1273.41
   185.3 1277.66     195 1282.31   204.8 1287.88   214.5  1294.4   224.2 1301.55
     234 1308.92   243.8 1316.22   253.5 1323.41   263.2 1330.49     273 1337.12
#Mann= 3 , 0 , 0
       0      .1       0     112    .045       0     122      .1       0
Bank Sta=112,122
XS Rating Curve= 0 ,0
Exp/Cntr=0.3,0.1

Type RM Length L Ch R = 1 ,8441    ,422,426.7,432.4
XS GIS Cut Line= 3
     1747581.946      147817.579     1747706.235      147874.531
      1747833.03      147924.977
#Sta/Elev= 30
     9.8 1279.69    19.5 1274.03    29.3 1269.49    39.1 1265.88    48.8 1262.76
    58.6 1259.99    68.4 1257.54    78.1 1255.31    87.9 1253.05    97.7 1250.69
   107.4  1247.9   117.2 1244.59     127 1241.77   131.7 1241.32   136.7 1240.84
   141.7 1241.26   146.5 1241.67   156.2 1243.68     166 1245.85   175.7 1247.72
   185.5 1249.51   195.2 1252.19   204.9 1256.29   214.7 1261.52   224.4 1267.17
   234.2 1272.97   243.9 1278.98   253.7  1285.1   263.4 1291.31   273.2 1297.64
#Mann= 3 , 0 , 0
       0     .08       0   131.7    .045       0   141.7     .08       0
Bank Sta=131.7,141.7
XS Rating Curve= 0 ,0
Exp/Cntr=0.3,0.1

Type RM Length L Ch R = 1 ,8014.3  ,364.8,373.3,381.8
XS GIS Cut Line= 3
     1747465.617      148182.572     1747613.378      148296.751
     1747703.541      148323.847
#Sta/Elev= 27
     9.8 1240.27    29.5  1238.3    39.3 1237.61    49.1 1237.29      59 1237.29
    68.8 1237.46    78.6 1237.53    88.5 1237.37    98.3 1236.84   108.1 1235.78
   117.9 1234.03   127.8 1231.81   132.6 1231.04   137.6 1230.25   142.6 1230.51
   147.4 1230.76   157.3 1233.08   176.9 1239.64   186.7 1243.04   196.1    1246
   205.6 1249.49   224.4 1256.93   233.8 1260.84   243.2 1264.96   252.6 1269.39
   262.1 1274.08   280.9 1283.67
#Mann= 3 , 0 , 0
       0      .1       0   132.6    .045       0   142.6      .1       0
Bank Sta=132.6,142.6
XS Rating Curve= 0 ,0
Exp/Cntr=0.3,0.1

Type RM Length L Ch R = 1 ,7641    ,400.6,400,398.7
XS GIS Cut Line= 3
     1747209.382      148352.977     1747273.896      148473.269
     1747338.411       148593.56
#Sta/Elev= 30
     9.7 1224.32    19.5 1223.76    29.2 1223.35      39 1222.98    48.7 1222.58
    58.5 1222.17    68.2 1221.84      78 1221.67    87.8 1221.54    97.5    1221
   107.2 1219.62     117 1217.49   126.7 1215.34   131.5 1214.84   136.5 1214.31
   141.5 1214.62   146.2 1214.91     156 1217.31   165.7 1220.64   175.5 1224.02
   185.2 1227.33     195 1230.57   204.7 1233.63   214.5  1236.6   224.2 1239.38
     234 1242.33   243.8 1245.29   253.5 1248.68   263.3 1252.59     273 1257.01
#Mann= 3 , 0 , 0
       0      .1       0   131.5    .045       0   141.5      .1       0
Bank Sta=131.5,141.5
XS Rating Curve= 0 ,0
Exp/Cntr=0.3,0.1

Type RM Length L Ch R = 1 ,7241    ,407.1,400,393.7
XS GIS Cut Line= 3
     1746834.879      148496.341     1746902.809      148614.712
     1746975.357      148730.484
#Sta/Elev= 30
     9.7 1244.26    19.5 1240.84    29.2 1236.97      39 1233.29    48.7 1229.49
    58.5  1225.8    68.2  1222.2      78 1218.71    87.7  1215.3    97.5 1211.95
   107.2 1208.66     117 1205.72   126.7    1204   131.5 1203.66   136.5 1203.29
   141.5 1203.36   146.2 1203.42     156 1204.54   165.8 1206.29   175.5 1207.78
   185.3 1209.14     195 1210.57   204.8 1212.38   214.5 1214.65   224.3 1217.22
   234.1 1219.78   243.8 1222.33   253.6 1224.87   263.3 1227.38   273.1 1230.01
#Mann= 3 , 0 , 0
       0      .1       0   131.5    .045       0   141.5      .1       0
Bank Sta=131.5,141.5
XS Rating Curve= 0 ,0
Exp/Cntr=0.3,0.1

Type RM Length L Ch R = 1 ,6841    ,553.3,558.1,562.8
XS GIS Cut Line= 3
     1746568.903      148847.729     1746673.569      148935.348
     1746778.236      149022.968
#Sta/Elev= 30
     9.8 1249.35    19.5 1245.23    29.2  1240.6      39 1235.59    48.8 1230.59
    58.5 1225.44    68.3 1219.78      78 1213.28    87.7 1207.42    97.5 1202.92
   107.3 1199.93     117 1198.03   126.8 1196.67   131.5 1196.41   136.5 1196.14
   141.5 1196.52   146.3 1196.88     156 1199.43   165.8 1202.84   175.5 1206.52
   185.3 1211.04     195 1216.34   204.8 1221.91   214.5 1227.39   224.2  1232.8
     234 1238.18   243.8 1243.53   253.5 1248.86   263.2 1254.18     273 1259.49
#Mann= 3 , 0 , 0
       0     .06       0   131.5    .045       0   141.5     .06       0
Bank Sta=131.5,141.5
XS Rating Curve= 0 ,0
Exp/Cntr=0.3,0.1

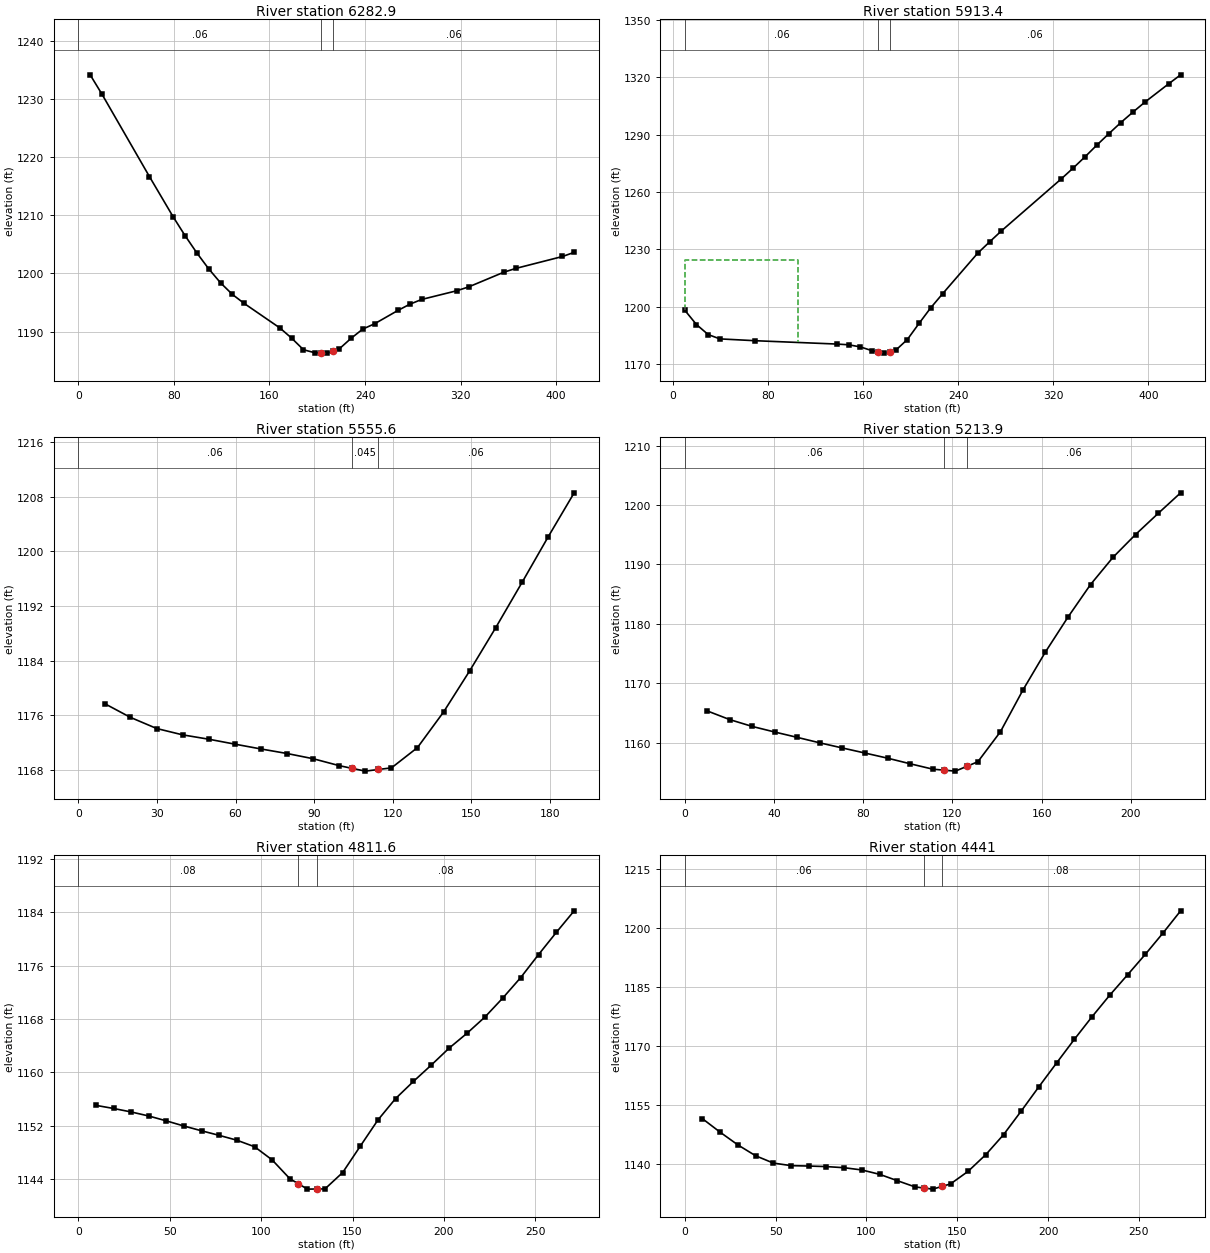
Type RM Length L Ch R = 1 ,6282.9  ,371.5,369.6,373.4
XS GIS Cut Line= 3
     1746140.248      149145.255     1746288.009      149344.509
     1746446.964      149396.001
#Sta/Elev= 30
     9.9 1234.13    19.8  1230.8    59.5 1216.66    79.4 1209.73    89.3 1206.52
    99.2 1203.54   109.1 1200.81   119.1 1198.39     129  1196.4   138.9 1194.85
   168.7 1190.65   178.6 1188.89   188.5  1186.9   198.5 1186.36   203.4 1186.34
   208.4 1186.32   213.4 1186.68   218.3 1187.02   228.2 1188.84   238.1 1190.45
   248.1 1191.37   267.7 1193.67   277.5 1194.72   287.4 1195.54   316.9 1197.04
   326.7 1197.69   356.2 1200.22     366 1200.86   405.3 1202.92   415.1 1203.63
#Mann= 3 , 0 , 0
       0     .06       0   203.4    .045       0   213.4     .06       0
Bank Sta=203.4,213.4
XS Rating Curve= 0 ,0
Exp/Cntr=0.3,0.1

Type RM Length L Ch R = 1 ,5913.4  ,356.1,357.8,359.5
XS GIS Cut Line= 3
     1745855.921      149315.404     1745967.861         149546.
     1746113.383      149635.552
#Sta/Elev= 30
     9.9 1198.19    19.7 1190.72    29.6 1185.46    39.4 1183.21      69 1182.26
     138  1180.5   147.9 1180.12   157.7    1179   167.6 1177.01   172.5  1176.4
   177.5 1175.76   182.5  1176.5   187.3 1177.21   197.2 1182.87     207 1191.27
   216.9 1199.48   226.8 1206.76   256.3 1227.96   266.4 1233.94   276.4 1239.71
   326.7 1266.88   336.7 1272.54   346.8 1278.49   356.8 1284.64   366.9 1290.61
   376.9 1296.38     387  1301.8     397 1306.99   417.1 1316.63   427.2 1321.34
#Mann= 3 , 0 , 0
     9.9     .06       0   172.5    .045       0   182.5     .06       0
#XS Ineff= 2 , 0
          104.87 1224.43
Permanent Ineff=
       F       F
Bank Sta=172.5,182.5
XS Rating Curve= 0 ,0
Exp/Cntr=0.3,0.1

Type RM Length L Ch R = 1 ,5555.6  ,337.7,341.6,345.6
XS GIS Cut Line= 2
     1745564.877      149498.986     1745632.041      149675.851
#Sta/Elev= 21
      10 1177.69    19.9 1175.66    29.9 1174.03    39.8  1173.1    49.8 1172.46
    59.7 1171.74    69.7 1171.03    79.7 1170.36    89.6  1169.6    99.6 1168.58
   104.5 1168.18   109.5 1167.78   114.5 1168.02   119.5 1168.26   129.4 1171.23
   139.4 1176.47   149.4 1182.53   159.3 1188.84   169.3 1195.45   179.2 1202.09
   189.2  1208.6
#Mann= 3 , 0 , 0
       0     .06       0   104.5    .045       0   114.5     .06       0
Bank Sta=104.5,114.5
XS Rating Curve= 0 ,0
Exp/Cntr=0.3,0.1

Type RM Length L Ch R = 1 ,5213.9  ,405,402.4,399.7
XS GIS Cut Line= 2
     1745258.161      149559.433     1745293.982      149778.836
#Sta/Elev= 24
    10.1 1165.36    20.2  1163.9    30.3 1162.75    40.4 1161.81    50.5 1160.91
    60.6 1159.99    70.7 1159.13    80.8 1158.28    90.9 1157.42     101 1156.48
   111.2 1155.57   116.3  1155.4   121.3 1155.24   126.3 1156.02   131.4 1156.82
   141.5 1161.86   151.6 1168.88   161.7 1175.29   171.8 1181.15   181.9 1186.62
     192 1191.21   202.1 1195.04   212.2 1198.58   222.3 1202.05
#Mann= 3 , 0 , 0
       0     .06       0   116.3    .045       0   126.3     .06       0
Bank Sta=116.3,126.3
XS Rating Curve= 0 ,0
Exp/Cntr=0.3,0.1

Type RM Length L Ch R = 1 ,4811.6  ,370.2,370.6,370.9
XS GIS Cut Line= 3
     1744839.506      149590.776     1744890.998      149756.447
     1744927.748      149847.015
#Sta/Elev= 30
     9.6 1155.06    19.3 1154.59    28.9 1154.07    38.6 1153.46    48.2 1152.73
    57.8 1151.96    67.5 1151.24    77.1 1150.56    86.7 1149.84    96.4 1148.86
     106 1146.89   115.7 1144.07   120.3 1143.32   125.3 1142.51   130.3 1142.53
   134.9 1142.54   144.6    1145   154.2 1148.94   163.9 1152.88   173.5 1156.07
   183.3 1158.65     193 1161.08   202.8 1163.63   212.6 1165.86   222.4 1168.29
   232.1 1171.12   241.9 1174.18   251.7 1177.64   261.5 1180.99   271.2  1184.2
#Mann= 3 , 0 , 0
       0     .08       0   120.3    .045       0   130.3     .08       0
Bank Sta=120.3,130.3
XS Rating Curve= 0 ,0
Exp/Cntr=0.3,0.1

Type RM Length L Ch R = 1 ,4441    ,395.9,400,404.1
XS GIS Cut Line= 3
     1744490.889      149705.989     1744528.805      149837.118
     1744566.722      149968.246
#Sta/Elev= 30
     9.7  1151.4    19.5 1147.95    29.3 1144.71      39 1141.97    48.7 1140.12
    58.5 1139.46    68.3 1139.36      78 1139.22    87.8 1138.93    97.5 1138.36
   107.3 1137.25     117 1135.64   126.8 1134.05   131.5 1133.78   136.5 1133.49
   141.5 1134.16   146.3 1134.81     156 1138.02   165.8 1142.29   175.5 1147.33
   185.3 1153.38     195 1159.54   204.8 1165.62   214.5 1171.58   224.3 1177.36
     234 1182.81   243.8 1187.98   253.5 1193.15   263.3  1198.6     273 1204.24
#Mann= 3 , 0 , 0
       0     .06       0   131.5    .045       0   141.5     .08       0
Bank Sta=131.5,141.5
XS Rating Curve= 0 ,0
Exp/Cntr=0.3,0.1

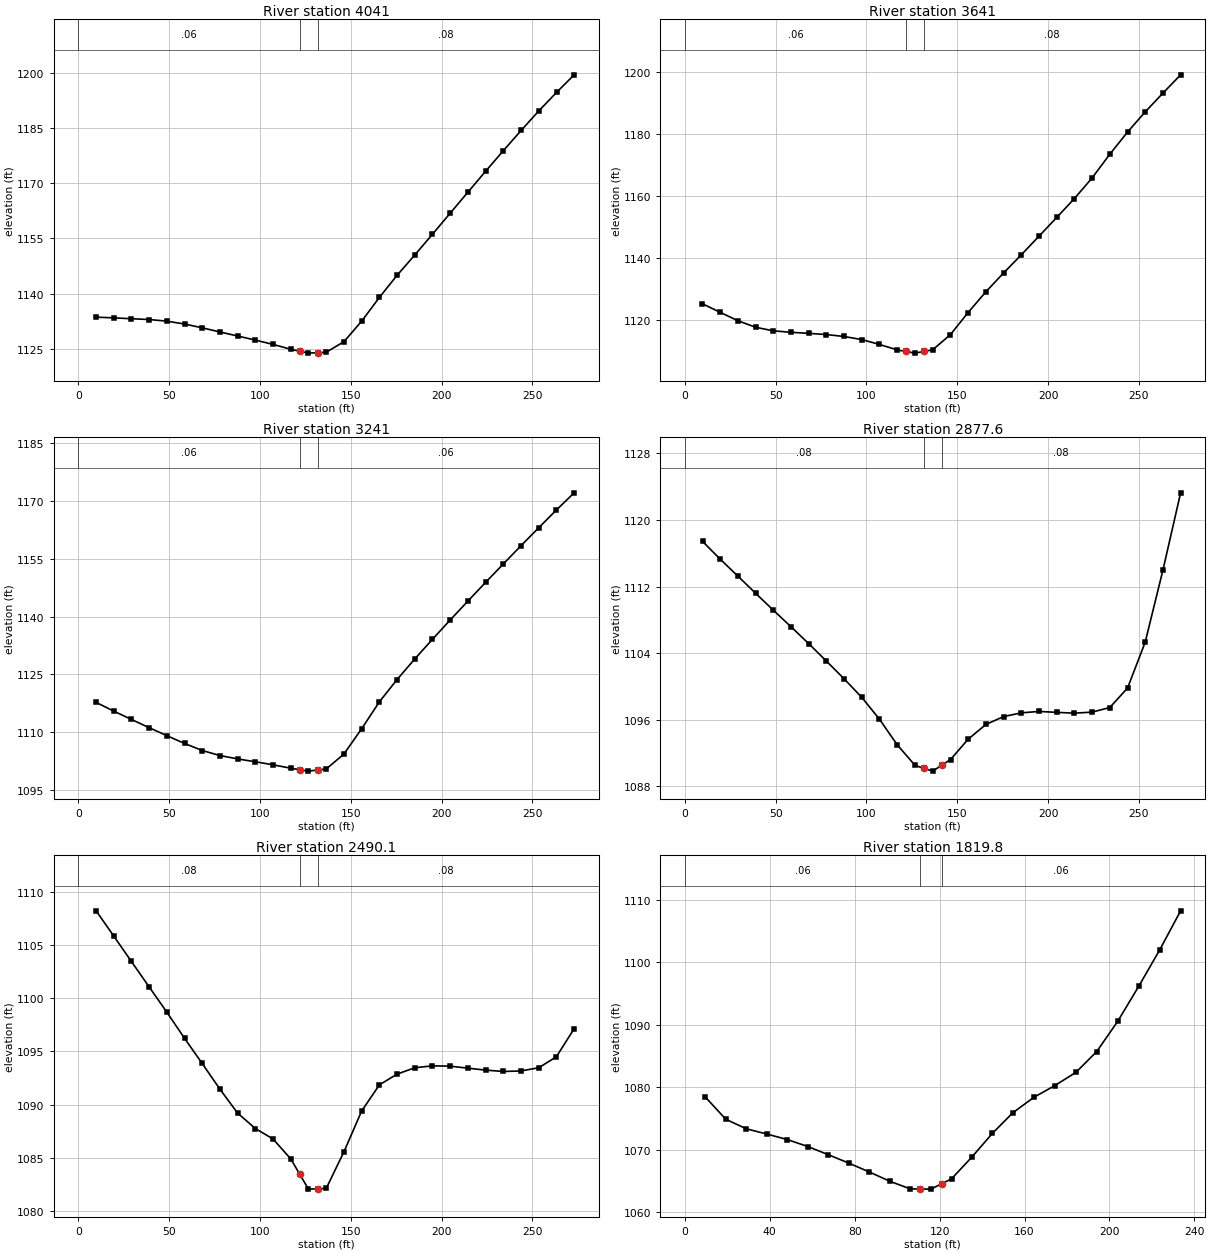
Type RM Length L Ch R = 1 ,4041    ,408.3,400,392
XS GIS Cut Line= 3
     1744121.733      149732.779     1744132.464      149868.856
     1744143.196      150004.934
#Sta/Elev= 30
     9.7 1133.61    19.5 1133.41    29.2 1133.18      39 1132.96    48.7 1132.52
    58.5 1131.74    68.3  1130.7      78 1129.58    87.8 1128.48    97.5 1127.37
   107.2 1126.21     117 1124.88   121.8 1124.37   126.7 1123.84   131.8 1123.97
   136.5 1124.08   146.3 1126.97     156 1132.52   165.8 1138.99   175.5 1144.97
   185.3 1150.51     195 1156.12   204.7  1161.8   214.5 1167.53   224.2 1173.19
     234 1178.79   243.8 1184.29   253.5 1189.58   263.3 1194.61     273 1199.39
#Mann= 3 , 0 , 0
       0     .06       0   121.8    .045       0   131.8     .08       0
Bank Sta=121.8,131.8
XS Rating Curve= 0 ,0
Exp/Cntr=0.3,0.1

Type RM Length L Ch R = 1 ,3641    ,401.9,400,397.8
XS GIS Cut Line= 3
     1743673.585      149797.367      1743738.14      149917.633
       1743800.8      150038.924
#Sta/Elev= 30
     9.7 1125.37    19.5  1122.6    29.2  1119.9      39 1117.79    48.7 1116.64
    58.5 1116.16    68.2 1115.83      78 1115.43    87.7 1114.82    97.5 1113.81
   107.2 1112.25     117 1110.48   121.7 1109.98   126.7 1109.45   131.7    1110
   136.5 1110.53   146.2 1115.38     156 1122.54   165.8 1129.25   175.5 1135.28
   185.3 1141.16     195 1147.14   204.8  1153.2   214.5 1159.28   224.3 1165.96
     234 1173.57   243.8 1180.75   253.5 1187.24   263.3  1193.3     273 1199.18
#Mann= 3 , 0 , 0
       0     .06       0   121.7    .045       0   131.7     .08       0
Bank Sta=121.7,131.7
XS Rating Curve= 0 ,0
Exp/Cntr=0.3,0.1

Type RM Length L Ch R = 1 ,3241    ,362.1,363.4,364.7
XS GIS Cut Line= 3
     1743318.806       150008.17     1743394.522      150121.745
     1743470.239       150235.32
#Sta/Elev= 30
     9.8 1117.76    19.5  1115.5    29.2 1113.36      39  1111.2    48.7 1109.15
    58.5 1107.11    68.3 1105.27      78 1103.98    87.8  1103.1    97.5 1102.36
   107.2 1101.58     117 1100.69   121.8 1100.32   126.7 1099.94   131.8 1100.23
   136.5  1100.5   146.2 1104.35     156 1110.94   165.7 1117.87   175.5  1123.7
   185.2    1129     195 1134.14   204.7 1139.11   214.5 1144.04   224.2 1148.87
     234 1153.66   243.7 1158.38   253.5 1163.06   263.2 1167.65     273 1172.11
#Mann= 3 , 0 , 0
       0     .06       0   121.8    .045       0   131.8     .06       0
Bank Sta=121.8,131.8
XS Rating Curve= 0 ,0
Exp/Cntr=0.3,0.1

Type RM Length L Ch R = 1 ,2877.6  ,388.3,387.5,386.6
XS GIS Cut Line= 3
     1743016.154      150192.528      1743084.46      150310.708
     1743152.766      150428.888
#Sta/Elev= 30
     9.8 1117.43    19.5  1115.3    29.3 1113.25      39  1111.2    48.7 1109.18
    58.5 1107.18    68.3 1105.14      78 1103.05    87.8 1100.91    97.5 1098.69
   107.2 1096.07     117 1092.99   126.8 1090.52   131.5 1090.19   136.5 1089.84
   141.5 1090.55   146.3 1091.23     156 1093.67   165.8 1095.45   175.5 1096.39
   185.3 1096.84     195 1097.01   204.8  1096.9   214.5  1096.8   224.3 1096.93
     234 1097.48   243.8 1099.83   253.5 1105.34   263.3 1114.03     273 1123.27
#Mann= 3 , 0 , 0
       0     .08       0   131.5    .045       0   141.5     .08       0
Bank Sta=131.5,141.5
XS Rating Curve= 0 ,0
Exp/Cntr=0.3,0.1

Type RM Length L Ch R = 1 ,2490.1  ,658.4,670.3,682.3
XS GIS Cut Line= 3
       1742679.8      150393.647     1742753.041      150508.834
     1742826.281      150624.022
#Sta/Elev= 30
     9.8  1108.2    19.5 1105.83    29.2 1103.45      39 1101.05    48.7 1098.69
    58.5 1096.22    68.2 1093.86      78 1091.44    87.7  1089.2    97.5 1087.75
   107.2 1086.77     117 1084.89   121.8 1083.49   126.7 1082.06   131.8 1082.09
   136.5 1082.13   146.2 1085.55     156  1089.4   165.8 1091.86   175.5 1092.86
   185.2 1093.46     195 1093.64   204.7 1093.61   214.5 1093.42   224.2 1093.24
     234 1093.11   243.7 1093.16   253.5 1093.46   263.2 1094.49     273 1097.13
#Mann= 3 , 0 , 0
       0     .08       0   121.8    .045       0   131.8     .08       0
Bank Sta=121.8,131.8
XS Rating Curve= 0 ,0
Exp/Cntr=0.3,0.1

Type RM Length L Ch R = 1 ,1819.8  ,224.8,223,221
XS GIS Cut Line= 3
      1742204.44      150687.788     1742199.291      150842.243
     1742208.917      150920.623
#Sta/Elev= 26
     9.7 1078.44    19.3  1074.9      29 1073.37    38.6 1072.54    48.3 1071.65
      58 1070.53    67.6 1069.23    77.3 1067.88    86.9 1066.47    96.6 1064.98
   106.2 1063.77   110.9 1063.75   115.9 1063.73   120.9 1064.58   125.6 1065.37
   135.2 1068.86   144.9 1072.66   154.5 1075.94   164.4 1078.41   174.3 1080.29
   184.2  1082.4     194 1085.73   203.9 1090.57   213.8 1096.17   223.6 1101.95
   233.5 1108.22
#Mann= 3 , 0 , 0
       0     .06       0   110.9    .045       0   120.9     .06       0
Bank Sta=110.9,120.9
XS Rating Curve= 0 ,0
Exp/Cntr=0.3,0.1

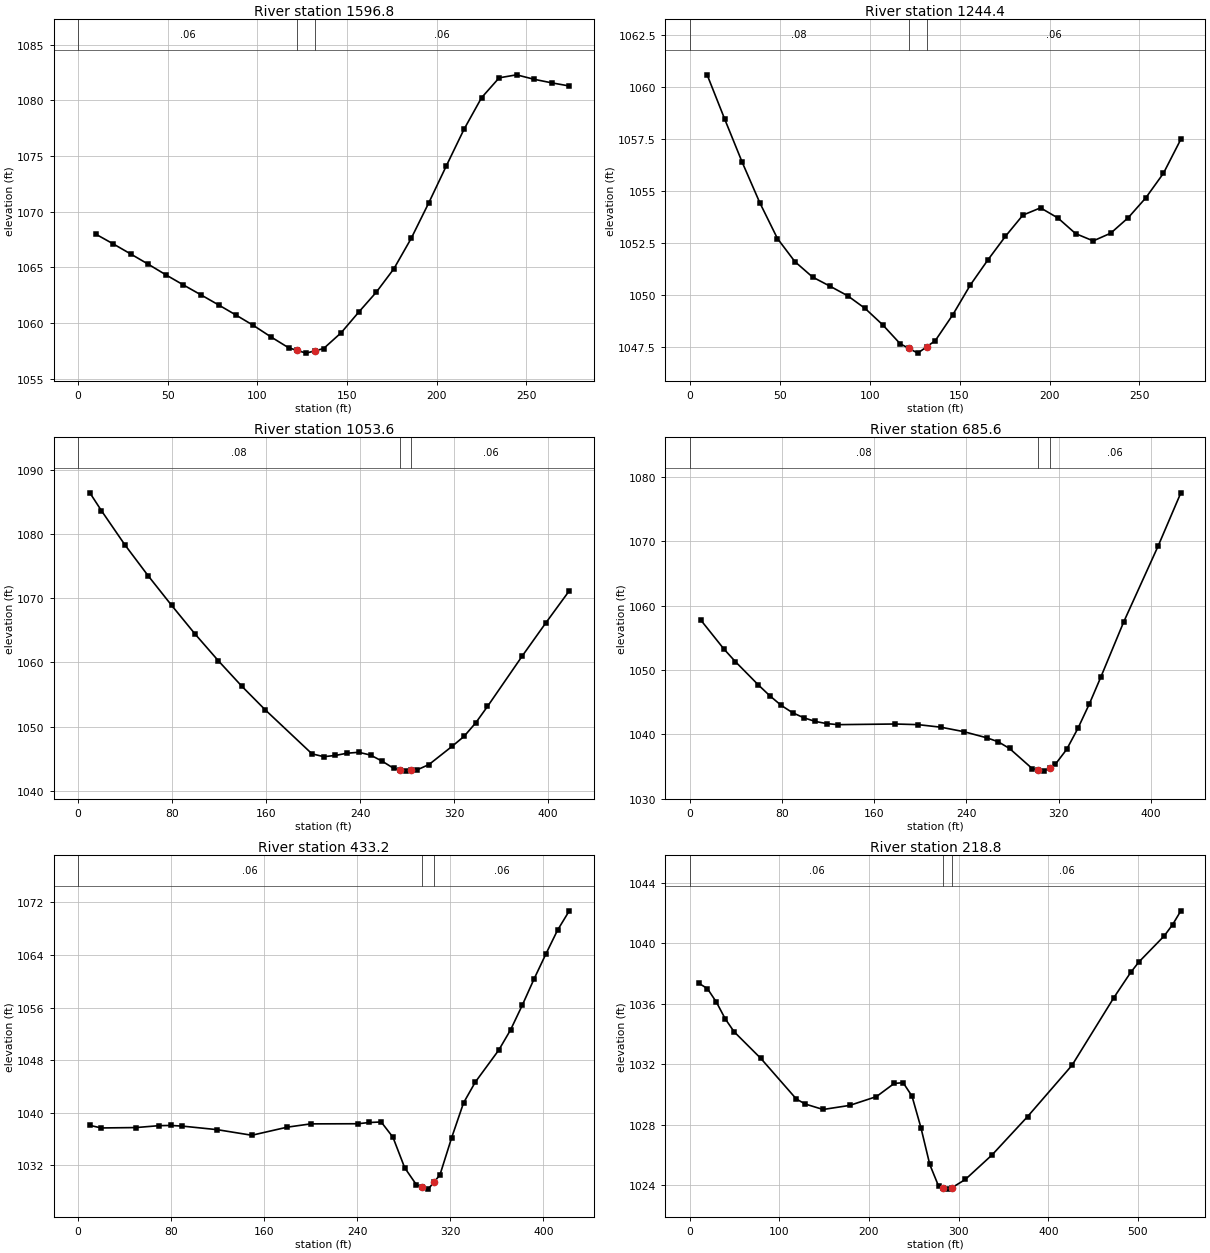
Type RM Length L Ch R = 1 ,1596.8  ,365.1,352.5,339.9
XS GIS Cut Line= 2
     1741973.843      150643.012     1741993.993      150916.145
#Sta/Elev= 30
     9.8 1067.99    19.6 1067.11    29.3 1066.21    39.1 1065.29    48.9 1064.34
    58.7 1063.43    68.5 1062.54    78.3 1061.64      88 1060.73    97.8 1059.79
   107.6 1058.76   117.4 1057.79   122.2 1057.55   127.2 1057.31   132.2 1057.52
   136.9 1057.72   146.7 1059.14   156.5 1060.99   166.3 1062.78   176.1 1064.88
   185.8 1067.62   195.6 1070.81   205.4 1074.13   215.2 1077.39     225 1080.23
   234.8 1082.01   244.5 1082.28   254.3 1081.88   264.1 1081.56   273.9 1081.28
#Mann= 3 , 0 , 0
       0     .06       0   122.2    .045       0   132.2     .06       0
Bank Sta=122.2,132.2
XS Rating Curve= 0 ,0
Exp/Cntr=0.3,0.1

Type RM Length L Ch R = 1 ,1244.4  ,192,190.8,189.5
XS GIS Cut Line= 3
     1741564.181      150765.381      1741652.24      150869.677
     1741740.299      150973.974
#Sta/Elev= 30
     9.7 1060.58    19.5 1058.44    29.2 1056.37      39 1054.42    48.8  1052.7
    58.5 1051.59    68.3 1050.85      78 1050.41    87.8 1049.95    97.5 1049.34
   107.3 1048.55     117 1047.64   121.8 1047.42   126.8 1047.19   131.8  1047.5
   136.5 1047.79   146.2 1049.03     156 1050.47   165.7 1051.67   175.5 1052.81
   185.2 1053.83     195 1054.18   204.7 1053.69   214.5 1052.94   224.3 1052.59
     234 1052.96   243.8 1053.71   253.5 1054.66   263.3 1055.84     273 1057.48
#Mann= 3 , 0 , 0
       0     .08       0   121.8    .045       0   131.8     .06       0
Bank Sta=121.8,131.8
XS Rating Curve= 0 ,0
Exp/Cntr=0.3,0.1

Type RM Length L Ch R = 1 ,1053.6  ,367.7,368,368.3
XS GIS Cut Line= 2
     1741333.547      150815.399     1741629.068      151110.921
#Sta/Elev= 29
      10  1086.4    19.9 1083.61    39.8 1078.31    59.7 1073.47    79.6 1068.88
    99.5 1064.43   119.4 1060.25   139.3  1056.3   159.2 1052.63     199 1045.78
     209 1045.34   218.9 1045.53   228.9 1045.88   238.8 1046.02   248.8 1045.59
   258.7 1044.64   268.7  1043.5   273.6  1043.3   278.6 1043.09   283.6 1043.19
   288.6  1043.3   298.5 1044.11   318.4 1046.98   328.4  1048.5   338.3  1050.6
   348.3 1053.15   378.1 1061.06     398 1066.17   417.9 1071.15
#Mann= 3 , 0 , 0
       0     .08       0   273.6    .045       0   283.6     .06       0
Bank Sta=273.6,283.6
XS Rating Curve= 0 ,0
Exp/Cntr=0.3,0.1

Type RM Length L Ch R = 1 ,685.6   ,259,252.4,245.8
XS GIS Cut Line= 2
     1741038.025      151010.175     1741329.069      151321.368
#Sta/Elev= 30
     9.9  1057.7    29.7 1053.25    39.6  1051.3    59.5 1047.68    69.4    1046
    79.3  1044.5    89.2 1043.35    99.1 1042.55     109 1041.99   118.9 1041.65
   128.8 1041.49   178.4 1041.59   198.2 1041.49     218 1041.09   237.8  1040.4
   257.6 1039.45   267.5 1038.84   277.5 1037.78   297.3 1034.63   302.2 1034.45
   307.2 1034.26   312.2 1034.79   317.1  1035.3     327 1037.63   336.9 1040.95
   346.8 1044.75   356.7  1048.9   376.5 1057.46   406.3 1069.24   426.1 1077.55
#Mann= 3 , 0 , 0
       0     .08       0   302.2    .045       0   312.2     .06       0
Bank Sta=302.2,312.2
XS Rating Curve= 0 ,0
Exp/Cntr=0.3,0.1

Type RM Length L Ch R = 1 ,433.2   ,215,214.4,213.8
XS GIS Cut Line= 3
     1740809.522      151315.763     1740953.737      151354.967
     1741192.503      151487.039
#Sta/Elev= 30
      10 1038.09    19.9 1037.69    49.8 1037.75    69.7 1038.04    79.7 1038.07
    89.7 1037.97   119.6 1037.43   149.4 1036.58   179.8 1037.81     200 1038.31
   240.4 1038.33   250.5 1038.52   260.6  1038.6   270.7 1036.28   280.8 1031.64
   290.9 1029.04     296 1028.71     301 1028.39     306 1029.46   311.1 1030.55
   321.2 1036.22   331.4  1041.5   341.5 1044.66   361.7 1049.53   371.8 1052.59
   381.9 1056.35     392 1060.33   402.1  1064.1   412.2 1067.75   422.3  1070.7
#Mann= 3 , 0 , 0
       0     .06       0     296    .045       0     306     .06       0
Bank Sta=296,306
XS Rating Curve= 0 ,0
Exp/Cntr=0.3,0.1

Type RM Length L Ch R = 1 ,218.8   ,216.9,218.8,220.7
XS GIS Cut Line= 3
     1740719.263      151478.951     1741099.859      151671.488
     1741220.754      151660.294
#Sta/Elev= 30
     9.9 1037.37    19.8    1037    29.8 1036.11    39.7    1035    49.6 1034.15
    79.4 1032.39     119 1029.71   128.9 1029.38   148.8 1029.02   178.5 1029.29
   208.3 1029.87   228.1 1030.74   238.1 1030.79     248  1029.9   257.9 1027.83
   267.8 1025.39   277.7 1023.95   282.7 1023.85   287.7 1023.76   292.7 1023.86
   307.5  1024.4   337.3 1026.02   376.9 1028.55   426.5 1031.94   473.2 1036.41
   491.9 1038.07   501.2 1038.77   529.3 1040.48   538.6 1041.22   547.9 1042.14
#Mann= 3 , 0 , 0
       0     .06       0   282.7    .045       0   292.7     .06       0
Bank Sta=282.7,292.7
XS Rating Curve= 0 ,0
Exp/Cntr=0.3,0.1

Chan Stop Cuts=-1
Use User Specified Reach Order=0